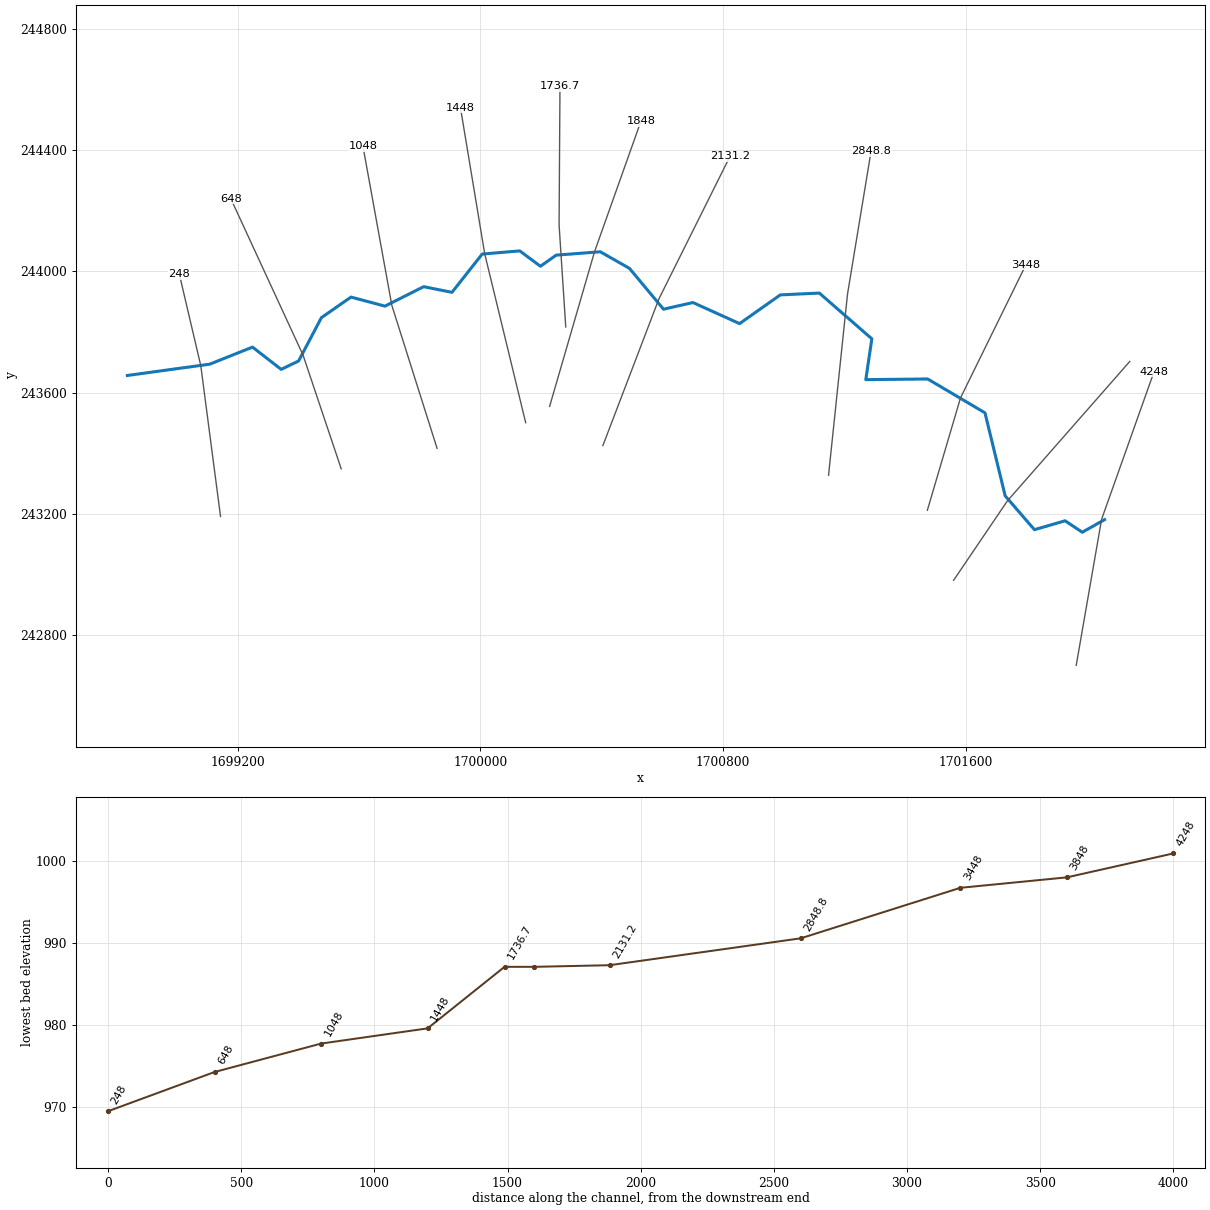
--- WForkRvTr.prj (project) ---

Proj Title=WForkRvTr
Current Plan=p01
Geom File=g01
Flow File=f01
Plan File=p01
DSS Export Rating Curves=0
DSS Export Rating Curve Sorted=0
DSS Export Volume Flow Curves=0
DXF OffsetX=0
DXF OffsetY=0
DXF ScaleX=0
DXF ScaleY=0

--- WForkRvTr.p01 (plan) ---

Plan Title=Floodplain
Program Version=4.00
Geom File=g01
Flow File=f01
K Sum by GR=0
Std Step Tol=0.01
Critical Tol=0.01
Num of Std Step Trials=20
Max Error Tol=0.3
Flow Tol Ratio=0.001
Split Flow NTrial=30
Split Flow Tol=0.02
Split Flow Ratio=0.02
Log Output Level=0
Friction Slope Method=1
Unsteady Friction Slope Method=2
Unsteady Bridges Friction Slope Method=1
Global Log Level=0
CheckData=False
Run HTab=0
Run UNet=0
Run PostProcess=0
UNET Theta=0
UNET Theta Warmup=0
UNET ZTol=0
UNET ZSATol=0
UNET MxIter=0
UNET MaxInSteps=0
UNET DtIC=0
UNET DtMin=0
UNET MaxCRTS=0
UNET WFStab=0
UNET SFStab=0
UNET WFX=0
UNET SFX=0
UNET DSS MLevel=0
UNET DZMax Abort=0
UNET Convert EG Bridges=0
UNET Use Existing IB Tables=0
UNET Froude Limit=0
UNET Froude Power=0
Write IC File=0
Echo Input=False
Echo Output=False
Write Detailed=0

--- WForkRvTr.f01 (steady flow) ---

Flow Title=NFF Regression Equation
Program Version=4.00
Number of Profiles=1
Profile Names=P100yr
River Rch & RM=WForkRvTr,Main      ,4248
726.2800
River Rch & RM=WForkRvTr,Main      ,248
800.5936
Boundary for River Rch & Prof#=WForkRvTr,Main      ,1
Up Type=0
Dn Type=3
Dn Slope=0.011745

--- WForkRvTr.g01 (geometry) ---

Geom Title=USGS 3m DEM
Program Version=4.00

River Reach=WForkRvTr     ,Main
Reach XY= 30
     1702058.282      243181.226     1701984.748      243139.715
     1701928.000      243177.464     1701826.965      243148.098
     1701730.539      243259.610     1701663.966      243533.277
     1701475.065      243644.926     1701271.115      243642.750
     1701290.925      243777.433     1701117.870      243928.117
     1700989.276      243922.126     1700855.017      243827.463
     1700701.345      243896.844     1700604.219      243874.952
     1700491.905      244009.561     1700395.883      244064.241
     1700250.430      244053.123     1700198.524      244016.479
     1700130.362      244067.184     1700006.509      244056.673
     1699906.895      243930.549     1699813.448      243949.152
     1699686.027      243885.070     1699573.984      243914.865
     1699476.479      243847.029     1699401.340      243704.242
     1699343.814      243676.639     1699249.338      243749.949
     1699108.209      243693.694     1698836.881      243656.482

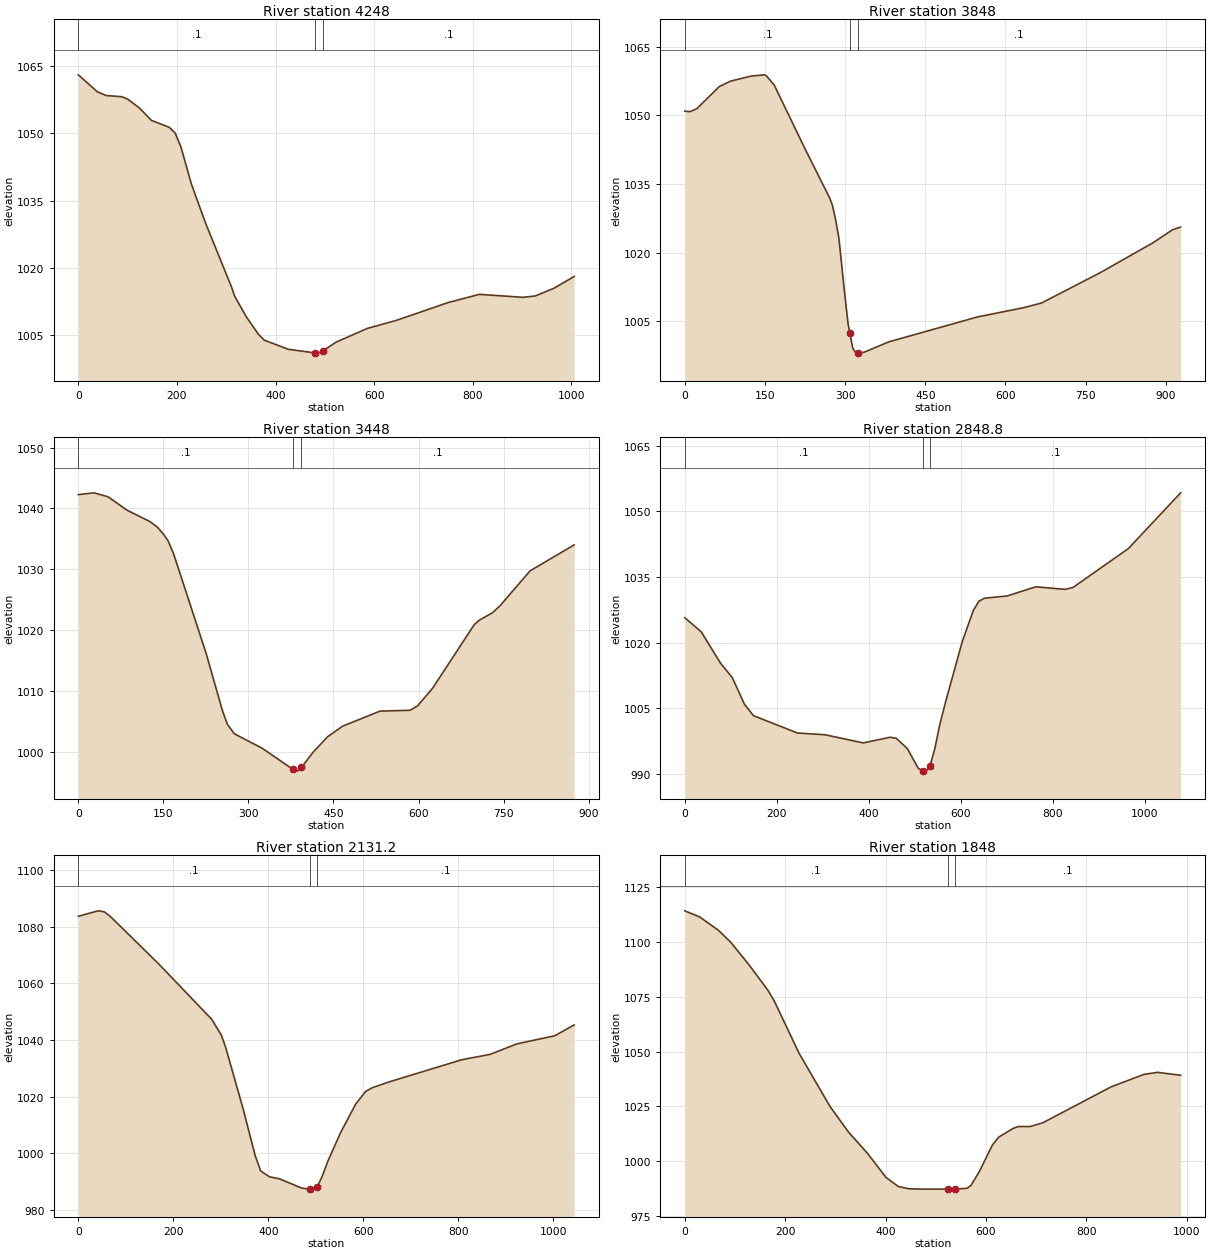
Type RM Length L Ch R = 1 ,4248,409.929,400,388.519
XS GIS Cut Line= 3
     1701964.718      242700.979     1702048.318      243182.071
     1702221.391      243669.341
#Sta/Elev= 30
       0 1063.02    38.8 1059.22    56.7 1058.40    88.0 1058.15   100.0 1057.61
   124.1 1055.61   148.2 1052.87   184.4 1051.32   196.4 1050.05   208.3 1046.85
   229.1 1038.74   256.7 1030.32   311.2 1015.56   316.9 1013.68   341.0 1009.03
   365.1 1005.20   377.2 1003.87   425.4 1001.86   480.8 1001.02   485.4 1000.99
   495.8 1001.49   522.9 1003.45   586.3 1006.51   644.1 1008.26   750.1 1012.27
   813.1 1014.09   901.3 1013.43   926.5 1013.73   964.3 1015.44  1005.4 1018.07
#Mann= 3 , 0 , 0
       0     0.1       0   480.8   0.045       0   495.8     0.1       0
Bank Sta=   480.8,   495.8
Exp/Cntr=0.3,0.1

Type RM Length L Ch R = 1 ,3848,393.547,400,405.356
XS GIS Cut Line= 3
     1701560.626      242981.369     1701737.941      243243.199
     1702141.334      243702.752
#Sta/Elev= 30
       0 1050.91     9.8 1050.79    22.3 1051.42    64.6 1056.28    85.8 1057.47
   124.5 1058.57   149.3 1058.84   153.2 1058.56   167.5 1056.57   224.9 1042.69
   271.3 1031.88   276.4 1030.27   282.2 1027.18   288.4 1023.12   297.5 1012.80
   305.5 1004.46   308.7 1002.56   314.1  999.23   318.3  998.39   323.7  998.16
   326.2  998.06   336.3  998.29   381.4 1000.51   547.3 1005.95   633.8 1007.98
   667.4 1009.00   776.8 1015.60   876.2 1022.17   912.2 1024.98   927.7 1025.60
#Mann= 3 , 0 , 0
       0     0.1       0   308.7   0.045       0   323.7     0.1       0
Bank Sta=   308.7,   323.7
Exp/Cntr=0.3,0.1

Type RM Length L Ch R = 1 ,3448,594.895,599.238,604.382
XS GIS Cut Line= 3
     1701474.035      243212.279     1701583.279      243582.600
     1701798.644      244020.939
#Sta/Elev= 30
       0 1042.25    27.7 1042.55    52.4 1041.90    85.8 1039.70   126.7 1037.80
   139.4 1036.91   151.4 1035.61   158.5 1034.61   168.0 1032.53   225.4 1016.15
   254.1 1006.75   262.9 1004.48   275.2 1002.92   324.7 1000.52   378.6  997.06
   386.1  996.78   393.6  997.39   414.4  999.92   439.6 1002.43   466.0 1004.17
   532.2 1006.65   585.1 1006.79   598.3 1007.51   624.8 1010.41   698.2 1020.86
   707.1 1021.60   730.6 1022.84   743.8 1023.98   796.7 1029.71   874.5 1033.99
#Mann= 3 , 0 , 0
       0     0.1       0   378.6   0.045       0   393.6     0.1       0
Bank Sta=   378.6,   393.6
Exp/Cntr=0.3,0.1

Type RM Length L Ch R = 1 ,2848.8,725.244,717.598,709.602
XS GIS Cut Line= 3
     1701148.288      243327.733     1701210.757      243924.518
     1701288.483      244395.689
#Sta/Elev= 30
       0 1025.68    35.6 1022.48    77.7 1015.27   103.0 1012.04   129.7 1005.90
   149.3 1003.28   244.8  999.32   304.5  998.92   388.1  997.05   446.2  998.35
   459.7  998.11   483.6  995.76   507.5  991.23   518.1  990.68   521.9  990.60
   531.3  991.19   533.1  991.86   543.0  995.55   554.3 1001.32   567.2 1006.57
   603.0 1020.22   627.1 1027.35   639.3 1029.47   651.1 1030.14   700.9 1030.67
   762.9 1032.76   826.6 1032.17   843.7 1032.61   964.0 1041.49  1077.6 1054.25
#Mann= 3 , 0 , 0
       0     0.1       0   518.1   0.045       0   533.1     0.1       0
Bank Sta=   518.1,   533.1
Exp/Cntr=0.3,0.1

Type RM Length L Ch R = 1 ,2131.2,281.431,283.165,283.448
XS GIS Cut Line= 3
     1700404.371      243425.376     1700589.107      243909.021
     1700823.788      244379.539
#Sta/Elev= 30
       0 1083.68    41.8 1085.60    54.5 1085.25    67.2 1083.64   168.9 1066.89
   280.8 1047.28   301.0 1041.68   310.2 1037.32   346.8 1015.67   372.2  999.17
   383.7  993.75   402.1  991.67   423.0  990.97   469.8  987.69   486.6  987.31
   487.4  987.31   494.1  987.31   502.4  988.09   512.5  991.50   525.0  997.13
   551.6 1007.14   583.5 1017.30   604.6 1021.81   618.9 1023.14   654.3 1025.19
   807.1 1033.01   866.8 1034.91   923.0 1038.61  1002.7 1041.47  1043.5 1045.30
#Mann= 3 , 0 , 0
       0     0.1       0   487.4   0.045       0   502.4     0.1       0
Bank Sta=   487.4,   502.4
Exp/Cntr=0.3,0.1

Type RM Length L Ch R = 1 ,1848,103.357,111.33,120.752
XS GIS Cut Line= 3
     1700228.774      243554.519     1700376.894      244064.475
     1700529.781      244494.651
#Sta/Elev= 30
       0 1114.29    29.8 1111.48    66.9 1105.41    91.6 1099.91   128.7 1089.39
   165.8 1077.90   178.1 1073.14   227.6 1049.20   289.4 1024.82   326.5 1013.07
   363.6 1003.56   400.7  992.47   425.4  988.29   446.8  987.26   474.9  987.11
   523.5  987.11   538.5  987.11   562.0  987.48   570.2  988.87   587.2  995.36
   612.4 1007.16   625.0 1010.83   653.8 1014.81   664.1 1015.70   688.0 1015.72
   713.2 1017.43   849.1 1033.84   914.8 1039.57   942.0 1040.47   987.6 1039.14
#Mann= 3 , 0 , 0
       0     0.1       0   523.5   0.045       0   538.5     0.1       0
Bank Sta=   523.5,   538.5
Exp/Cntr=0.3,0.1

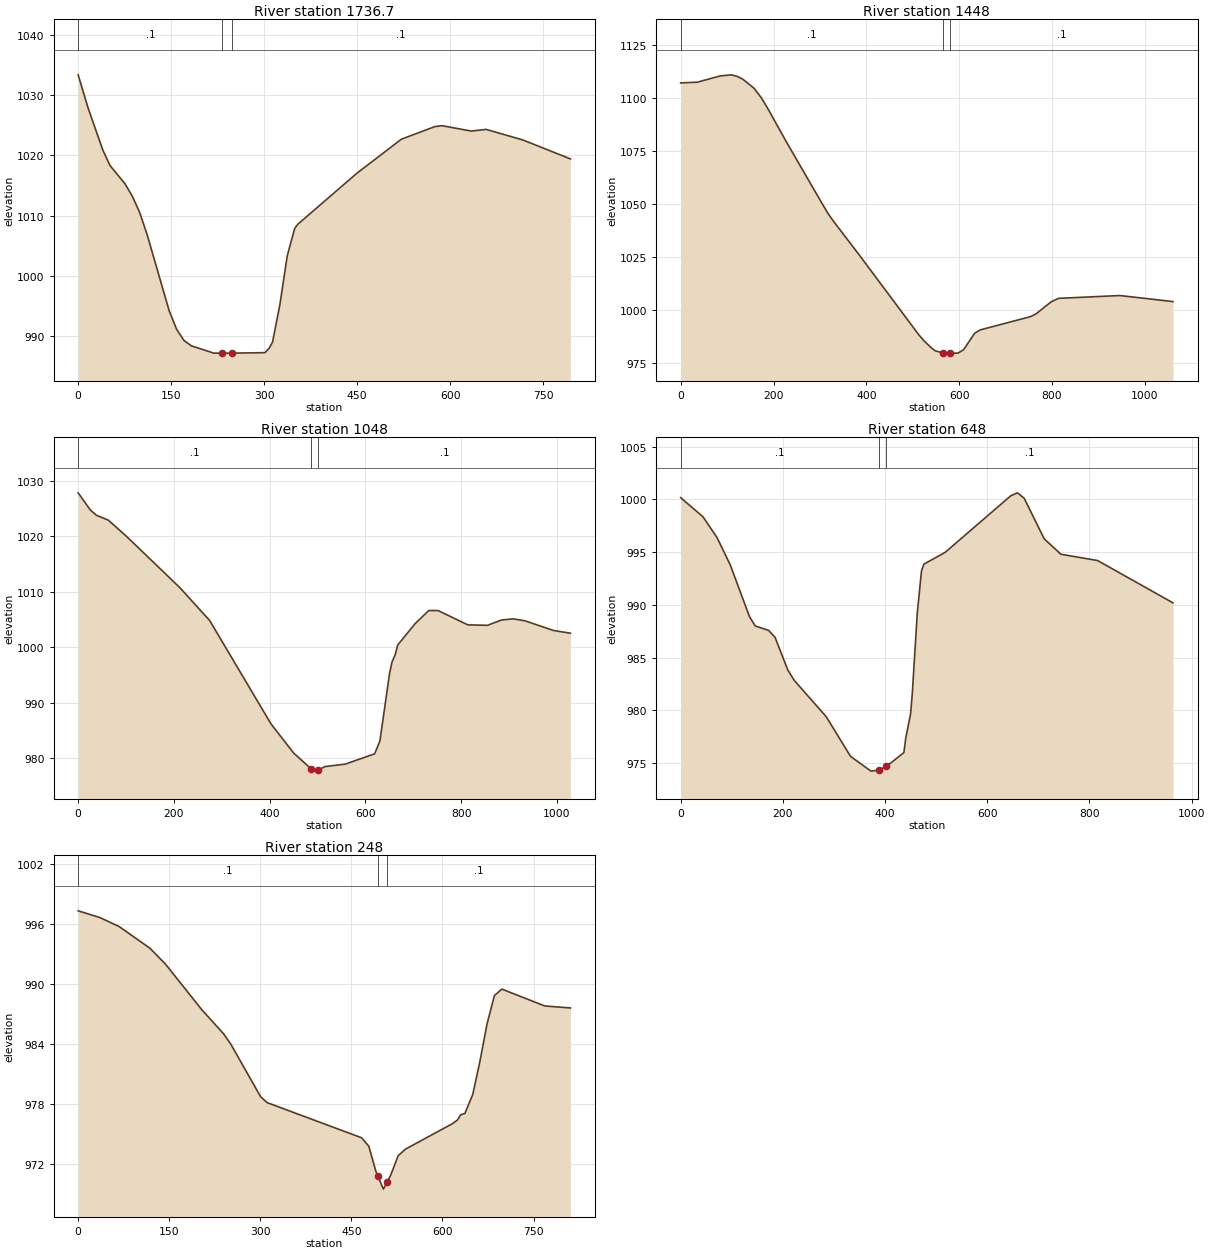
Type RM Length L Ch R = 1 ,1736.7,284.319,288.67,291.359
XS GIS Cut Line= 3
     1700281.980      243816.514     1700260.005      244152.928
     1700262.930      244609.455
#Sta/Elev= 30
       0 1033.42    16.0 1027.91    39.8 1020.90    51.3 1018.34    75.5 1015.29
    87.3 1013.24    99.2 1010.51   111.1 1006.87   146.8  994.14   158.7  991.09
   170.6  989.22   182.5  988.33   218.8  987.11   232.7  987.11   247.7  987.11
   301.5  987.19   308.2  987.96   313.4  988.94   325.3  995.19   337.1 1003.28
   349.1 1007.85   353.9 1008.53   449.5 1017.05   521.2 1022.71   574.7 1024.79
   586.5 1024.96   634.0 1024.06   657.8 1024.34   717.1 1022.58   793.7 1019.43
#Mann= 3 , 0 , 0
       0     0.1       0   232.7   0.045       0   247.7     0.1       0
Bank Sta=   232.7,   247.7
Exp/Cntr=0.3,0.1

Type RM Length L Ch R = 1 ,1448,398.027,400,400.627
XS GIS Cut Line= 3
     1700149.873      243500.839     1700014.763      244057.774
     1699934.933      244538.804
#Sta/Elev= 30
       0 1107.02    35.8 1107.35    84.7 1110.29   108.7 1110.83   121.3 1110.13
   133.5 1108.82   158.0 1104.52   174.3 1099.84   190.4 1093.91   226.7 1079.59
   304.6 1050.16   316.8 1045.65   329.0 1041.84   384.0 1026.09   513.0  988.25
   524.5  985.33   541.3  981.84   548.9  980.63   565.6  979.68   580.6  979.61
   597.4  979.58   609.4  981.14   633.5  988.97   645.6  990.54   753.9  996.80
   765.9  998.13   797.8 1003.70   814.0 1005.42   946.4 1006.74  1060.7 1003.89
#Mann= 3 , 0 , 0
       0     0.1       0   565.6   0.045       0   580.6     0.1       0
Bank Sta=   565.6,   580.6
Exp/Cntr=0.3,0.1

Type RM Length L Ch R = 1 ,1048,401.205,400,399.524
XS GIS Cut Line= 3
     1699857.794      243416.197     1699708.641      243887.685
     1699613.260      244413.028
#Sta/Elev= 30
       0 1027.84    25.6 1024.74    38.1 1023.80    63.0 1022.92   100.4 1020.05
   212.4 1010.77   274.7 1004.85   402.8  986.24   450.1  980.99     487  978.10
   498.7  977.72     502  977.89   515.0  978.53   558.4  978.99   619.4  980.84
   630.4  983.14   650.8  995.43   655.6  997.34   662.4  998.71   667.6 1000.43
   703.8 1004.26   732.5 1006.64   752.1 1006.63   814.2 1004.06   855.1 1003.98
   884.8 1004.94   909.0 1005.14   933.1 1004.80   993.4 1003.04  1028.4 1002.56
#Mann= 3 , 0 , 0
       0     0.1       0     487   0.045       0     502     0.1       0
Bank Sta=     487,     502
Exp/Cntr=0.3,0.1

Type RM Length L Ch R = 1 ,648,403.486,400,401.05
XS GIS Cut Line= 3
     1699541.812      243348.769     1699416.068      243723.367
     1699177.889      244239.259
#Sta/Elev= 30
       0 1000.16    43.6  998.35    71.2  996.37    96.9  993.80   134.5  988.90
   145.8  988.00   172.1  987.58   184.6  986.93   209.6  983.83   222.1  982.85
   284.8  979.40   332.4  975.64   372.4  974.24   387.6  974.34   402.6  974.68
   436.8  976.00   440.5  977.37   449.9  979.66   453.3  981.62   463.0  989.21
   471.2  993.20   476.0  993.86   517.4  994.97   646.0 1000.34   659.1 1000.62
   672.2 1000.11   711.4  996.26   744.0  994.80   816.0  994.20   963.4  990.19
#Mann= 3 , 0 , 0
       0     0.1       0   387.6   0.045       0   402.6     0.1       0
Bank Sta=   387.6,   402.6
Exp/Cntr=0.3,0.1

Type RM Length L Ch R = 1 ,248,258.639,248.037,235.179
XS GIS Cut Line= 3
     1699143.979      243191.526     1699078.948      243688.294
     1699008.237      243989.810
#Sta/Elev= 30
       0  997.35    35.7  996.68    67.6  995.77   118.2  993.60   143.5  992.03
   203.3  987.46   239.3  985.03   251.2  984.00   300.5  978.71   311.1  978.12
   466.8  974.59   478.7  973.74   490.2  971.25   493.5  970.75   502.7  969.44
   508.5  970.11   514.9  970.87   527.1  972.80   539.3  973.46   616.0  975.99
   624.7  976.37   630.1  976.90   636.9  977.03   649.8  978.92   661.3  982.14
   673.5  986.03   685.6  988.86   697.8  989.50   768.4  987.81   810.7  987.61
#Mann= 3 , 0 , 0
       0     0.1       0   493.5   0.045       0   508.5     0.1       0
Bank Sta=   493.5,   508.5
Exp/Cntr=0.3,0.1